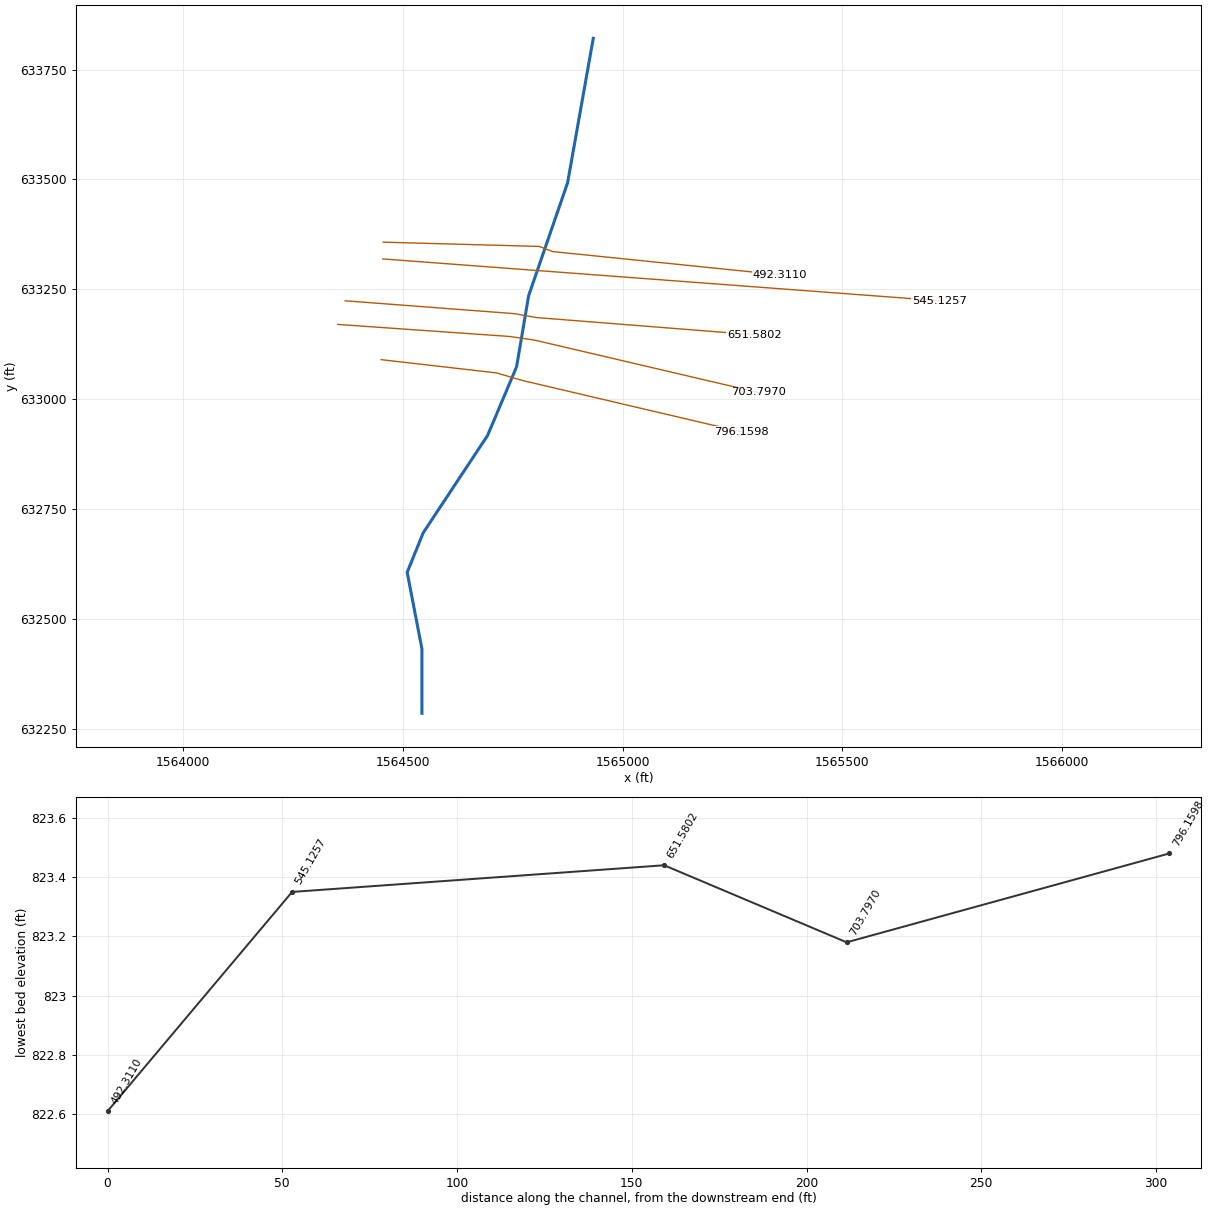
--- GRE-68TAF.prj (project) ---

Proj Title=GRE-68-12.65 TAF
Current Plan=p02
Default Exp/Contr=0.3,0.1
English Units
Geom File=g01
Geom File=g02
Geom File=g03
Flow File=f01
Plan File=p01
Plan File=p02
Y Axis Title=Elevation
X Axis Title(PF)=Main Channel Distance
X Axis Title(XS)=Station
BEGIN DESCRIPTION:
END DESCRIPTION:
DSS Export Rating Curves= 0
DSS Export Rating Curve Sorted= 0
DSS Export Volume Flow Curves= 0
DXF OffsetX= 0
DXF OffsetY= 0
DXF ScaleX= 1
DXF ScaleY= 10

--- GRE-68TAF.p02 (plan) ---

Plan Title=ProposedTAF
Program Version=6.41
Short Identifier=PropTAF
Geom File=g03
Flow File=f01
Subcritical Flow
K Sum by GR= 0
Std Step Tol= 0.01
Critical Tol= 0.01
Num of Std Step Trials= 20
Max Error Tol= 0.3
Flow Tol Ratio= 0.001
Split Flow NTrial= 30
Split Flow Tol= 0.02
Split Flow Ratio= 0.02
Log Output Level= 0
Friction Slope Method= 1
Unsteady Friction Slope Method= 2
Unsteady Bridges Friction Slope Method= 1
Parabolic Critical Depth
Global Vel Dist= 0 , 0 , 0
Global Log Level= 0
CheckData=True
Encroach Param=-1 ,0,0, 0
Flow Ratio Tolerance=0.1
Flow Ratio Min Ratio=0.5
Flow Ratio Max Ratio=4
Flow Ratio Max Iterations= 10
Computation Interval=1MIN
Output Interval=1HOUR
Instantaneous Interval=1HOUR
Mapping Interval=1HOUR
Computation Time Step Use Courant=        0
Computation Time Step Use Time Series=    0
Computation Time Step Count To Double=0
Computation Time Step Max Doubling=0
Computation Time Step Max Halving=0
Computation Time Step Residence Courant=0
Run HTab= 0
Run UNet= 0
Run Sediment= 0
Run PostProcess= 0
Run WQNet= 0
Run RASMapper= 0
UNET Theta= 1
UNET Theta Warmup= 1
UNET ZTol= 0.02
UNET ZSATol= 0.02
UNET MxIter= 20
UNET Max Iter WO Improvement= 0
UNET MaxInSteps= 0
UNET DtIC= 0
UNET DtMin= 0
UNET MaxCRTS= 20
UNET WFStab= 2
UNET SFStab= 1
UNET WFX= 1
UNET SFX= 1
UNET Gravity=32.17405
UNET 1D Methodology=Finite Difference
UNET DSS MLevel= 4
UNET Pardiso=0
UNET DZMax Abort= 100
UNET Use Existing IB Tables=-1
UNET Froude Reduction=False
UNET Froude Limit= 0.8
UNET Froude Power= 4
UNET D1 Cores= 0
UNET WindReference=Eulerian
UNET WindDragFormulation=Hsu (1988)
UNET D2 Coriolis=0
UNET D2 Cores= 0
UNET D2 Theta= 1
UNET D2 Theta Warmup= 1
UNET D2 Z Tol= 0.01
UNET D2 Volume Tol= 0.01
UNET D2 Max Iterations= 20
UNET D2 Equation= 0
UNET D2 RampUpFraction=0.1
UNET D2 TimeSlices= 1
UNET D2 Turbulence Formulation=None
UNET D2 Eddy Viscosity=0.3
UNET D2 Transverse Eddy Viscosity=0.1
UNET D2 Smagorinsky Mixing=0.05
UNET D2 BCVolumeCheck=0
UNET D2 Cores=0
UNET D2 SolverType=PARDISO (Direct)
UNET D2 Minimum Iterations= 3
UNET D2 Maximum Iterations= 30
UNET D2 Restart Number= 10
UNET D2 Relaxation Coeff=1.3
UNET D2 SOR Precondition Iterations= 10
UNET D2 ILUT Maximum Fill= 8
UNET D2 ILUT Tolerance=1E-08
UNET D2 Convergence Tolerance=0.00001
UNET D1D2 MaxIter= 0
UNET D1D2 ZTol=0.01
UNET D1D2 QTol=0.1
UNET D1D2 MinQTol=1
Write IC File= 0
Write IC File at Fixed DateTime=0
Write IC File at Sim End=0
Echo Input=False
Echo Parameters=False
Echo Output=False
Write Detailed= 0
HDF Write Warmup=0
HDF Write Time Slices=0
HDF Flush=0
HDF Compression= 1
HDF Chunk Size= 1
HDF Spatial Parts= 1
HDF Use Max Rows=0
HDF Fixed Rows= 1
Calibration Method= 0
Calibration Iterations= 20
Calibration Max Change=0.05
Calibration Tolerance=0.2
Calibration Maximum=1.5
Calibration Minimum=0.5
Calibration Optimization Method= 1
WQ AD Non Conservative
WQ ULTIMATE=-1
WQ Max Comp Step=1HOUR
WQ Output Interval=15MIN
WQ Output Selected Increments= 0
WQ Create Restart=0
WQ Fixed Restart=0
WQ System Summary=0
WQ Write To DSS=0
Sorting and Armoring Iterations= 10
XS Update Threshold= 0.02
Bed Roughness Predictor= 0
Hydraulics Update Threshold= 0.02
Energy Slope Method= 1
Volume Change Method= 1
Sediment Retention Method= 0
Sediment TS Multiplier= 1
Warm Up Method= 0
XS Weighting Method= 0
Number of US Weighted Cross Sections= 1
Number of DS Weighted Cross Sections= 1
Upstream XS Weight=0
Main XS Weight=1
Downstream XS Weight=0
Number of DS XS's Weighted with US Boundary= 1
Upstream Boundary Weight= 1
Weight of XSs Associated with US Boundary= 0
Number of US XS's Weighted with DS Boundary= 1
Downstream Boundary Weight= 0.5
Weight of XSs Associated with DS Boundary= 0.5
Percentile Method= 0
Sediment Output Level= 3
Mass or Volume Output= 0
Output Increment Type= 1
Profile and TS Output Increment= 1
Transport Output Increment 1
XS Output Flag= 0
XS Output Increment= 10
Read HDF5 Sediment Hotstart= 0
Sediment Hotstart Type= 0
Write Gradation File= 0
Read Gradation Hotstart= 0
Write HDF5 File= 1
Write Binary Output= 1
Write DSS Sediment File= 0
DSS Sediment Output Type= 1
SV Curve= 0
Specific Gage Flag= 0
Subcell Erosion Methods= 0
Subcell Deposition Methods= 0
Advection Scheme= 1
Matrix Solver= 0
Implicit Weighting Factor= 1
Maximum Outer Loop Convergence Iterations= 5
Convergence Maximum Absolute= 0.001
Convergence RMSE= 0.0001
Grain Fractions Max Abs Error= 0.001
Max Subgrid Regions= 1
Max Subgrid Length Scale= 3.402823E+38
Initial Layer Thickness= 3
Min Layer Thickness= 0.1
Max Layer Thickness= 6
Number of Layers= 5

--- GRE-68TAF.p01 (plan) ---

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Plan Title=Existing
Short Identifier=Exist
Geom File=g02
Flow File=f01

--- GRE-68TAF.f01 (steady flow) ---

Flow Title=TAF
Program Version=6.41
Number of Profiles= 7
Profile Names=2xHMMF,2-yr,5-yr,10-yr,25-yr,50-yr,100-yr
River Rch & RM=Oldtown Creek,Reach           ,796.1598
    38.6     620    1070    1180    1465    1740    2000
Boundary for River Rch & Prof#=Oldtown Creek,Reach           , 1
Up Type= 0
Dn Type= 3
Dn Slope=0.000457
Boundary for River Rch & Prof#=Oldtown Creek,Reach           , 2
Up Type= 0
Dn Type= 3
Dn Slope=0.000457
Boundary for River Rch & Prof#=Oldtown Creek,Reach           , 3
Up Type= 0
Dn Type= 3
Dn Slope=0.000457
Boundary for River Rch & Prof#=Oldtown Creek,Reach           , 4
Up Type= 0
Dn Type= 3
Dn Slope=0.000457
Boundary for River Rch & Prof#=Oldtown Creek,Reach           , 5
Up Type= 0
Dn Type= 3
Dn Slope=0.000457
Boundary for River Rch & Prof#=Oldtown Creek,Reach           , 6
Up Type= 0
Dn Type= 3
Dn Slope=0.000457
Boundary for River Rch & Prof#=Oldtown Creek,Reach           , 7
Up Type= 0
Dn Type= 1
Dn Known WS=831.3
DSS Import GetInterval= 0
DSS Import GetPeak= 0
DSS Import FillOption= 0

--- GRE-68TAF.g03 (geometry) ---

Geom Title=ProposedTAF2
Program Version=6.41

River Reach=Oldtown Creek   ,Reach
Reach XY= 9
1564542.97678225 632284.974284071564542.97678225 632431.72946916
1564509.36747808 632606.001251451564546.03217354 632696.19454229
1564692.43591249 632917.586620361564758.38186807 633073.78340392
1564785.88038966 633235.825587461564874.48673702 633492.64716136
1564932.87995289  633821.2389797

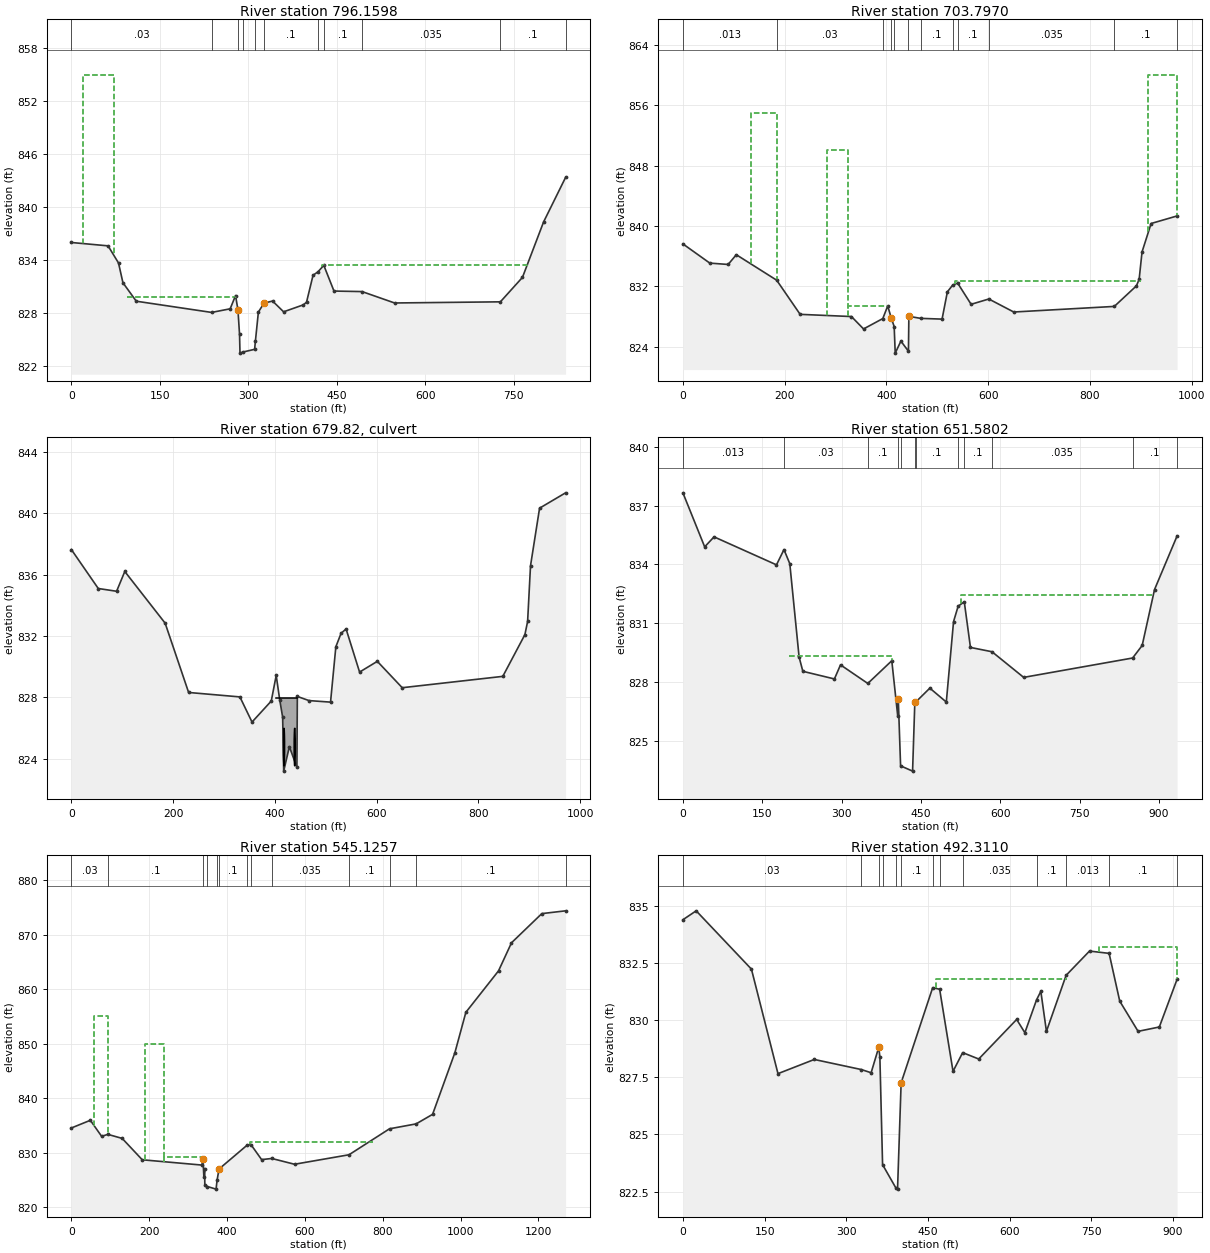
Type RM Length L Ch R = 1 ,796.1598,96.02,92.36,85.26
XS GIS Cut Line= 4
1564450.37706531 633089.955505171564712.68526857 633059.81850759
1564772.71289077 633042.299422491565270.44192485 632925.50552181
#Sta/Elev= 30
       0  836.01    62.2  835.63   79.91  833.69   87.41  831.45  110.04  829.36
  237.74  828.09  269.19   828.5  278.33     830  282.39  828.37  285.09  825.59
  285.85  823.48  290.56   823.6  310.63  823.91  312.07   824.9  317.02  828.13
  326.57  829.14  341.05  829.38  359.77  828.16  393.33  828.95  398.65  829.25
  409.71   832.3  418.01  832.69  427.95  833.42  445.19  830.51  492.79  830.45
  547.92  829.16  727.29  829.29  764.71  832.06  800.54  838.34  837.81  843.38
#Mann= 11 ,-1,0
       0     .03       0  237.74      .1       0  282.39     .07       0
  290.56     .06       0  312.07     .07       0  326.57      .1       0
  418.01    .013       0  427.95      .1       0  492.79    .035       0
  727.29      .1       0  837.81      .1       0
#XS Ineff= 3 ,-1
      20      73     855      95     279   829.8     425     775   833.5
Permanent Ineff=
       T       F       F
Bank Sta=282.39,326.57
XS Rating Curve= 0 ,0
Exp/Cntr=0.3,0.1

Type RM Length L Ch R = 1 ,703.7970,56.86,52.22,53.96
XS GIS Cut Line= 4
1564351.57189531 633170.133788931564742.66198021 633142.73948771
1564799.61447382 633134.423360561565307.72604505 633015.41407765
#Sta/Elev= 30
       0  837.63   52.88  835.09   88.91  834.91  104.99   836.2  184.32  832.83
  230.47  828.31  331.27  828.02   355.1  826.38  392.91  827.75  402.62  829.42
  409.74  827.79  415.29   826.7  417.35  823.18  428.51  824.77  443.35  823.43
  444.18  828.05   467.2  827.78  509.44  827.68  519.88  831.29  530.18  832.17
     540  832.45  566.53  829.64   601.4  830.34  650.33  828.62  848.05  829.36
  891.48  832.08  896.83  832.94  902.53  836.57  920.35  840.33  971.47  841.33
#Mann= 12 ,-1,0
       0    .013       0  184.32     .03       0  392.91      .1       0
  409.74     .07       0  415.29     .06       0  443.35     .07       0
   467.2      .1       0  530.18    .013       0     540      .1       0
   601.4    .035       0  848.05      .1       0  971.47      .1       0
#XS Ineff= 5 ,-1
     133     184     855     284     325     850     325   402.5   829.4
     535     900  832.73     915     971     860
Permanent Ineff=
       T       T       F       F       T
Bank Sta=409.74,444.18
XS Rating Curve= 0 ,0
Exp/Cntr=0.3,0.1

Type RM Length L Ch R = 2 ,679.82  ,,,
Bridge Culvert--1,0,-1,-1, 0
Deck Dist Width WeirC Skew NumUp NumDn MinLoCord MaxHiCord MaxSubmerge Is_Ogee
0.5,51,2.6,0, 2, 3, , , 0.98, 0, 2,2,,
  402.62  444.18
  827.96  827.96
     820     820
  394.87  438.42     460
  827.96  827.96  827.46
     820     820     820
BR Coef=-1 , 0 , 0 ,, 0 ,,,0.8,-1,,0,
WSPro=,,,, 1 ,,,, 0 ,,,, 0 ,,,,-1 ,-1 ,-1 , 0 , 0 , 0 , 0 , 0
Multiple Barrel Culv=1,2.5,2.5,51,0.019,0.9,1,2,3,823.5,823.5, 2,Culvert #1  , 0 ,1
     418     412     439     431
BC Culvert Barrel=1,1,0
BC Culvert Barrel=2,2,0
Culvert Bottom n=0.019
Culvert Bottom Depth=1.5
BC Design=,, 0 ,, 0 ,,,,,,
BC Use User HTab Curves=0
BC User HTab FreeFlow(D)= 0

Type RM Length L Ch R = 1 ,651.5802,111.44,106.45,103.86
XS GIS Cut Line= 4
1564368.19322392 633223.944023461564754.39468275 633194.59298644
1564803.28094337 633185.787675341565298.98762597 633146.65295931
#Sta/Elev= 30
       0  837.66   41.14   834.9    58.9  835.41  176.92  833.98  191.05  834.76
  202.06  834.04  219.65  829.27  226.73  828.54  286.43  828.15  297.93  828.87
  349.54  827.92  394.87  829.08  406.18  826.24  407.14  827.12  411.51  823.71
  434.17  823.44  438.42  826.95  440.53  826.98  466.79  827.68  497.94  826.97
  511.62  831.08  520.34  831.87  531.91  832.09  543.58  829.76  584.31  829.54
  644.17  828.23  850.17  829.22  868.19  829.86  891.58  832.72  934.24  835.46
#Mann= 12 ,-1,0
       0    .013       0  191.05     .03       0  349.54      .1       0
  407.14     .07       0  411.51     .06       0  438.42     .07       0
  440.53      .1       0  520.34    .013       0  531.91      .1       0
  584.31    .035       0  850.17      .1       0  934.24      .1       0
#XS Ineff= 2 ,-1
     200     395   829.3     526     891  832.46
Permanent Ineff=
       F       F
Bank Sta=407.14,438.42
XS Rating Curve= 0 ,0
Exp/Cntr=0.3,0.1

Type RM Length L Ch R = 1 ,545.1257,46.6,52.81,53.82
XS GIS Cut Line= 2
1564453.88126293  633319.22246731565720.03325592 633224.16122113
#Sta/Elev= 30
       0  834.56   48.72  835.97   77.73  833.03   93.68  833.39  130.52  832.65
  182.09  828.73  335.39  827.76  338.01  828.94  340.42   825.6  342.39  827.13
  342.86  824.13  349.28  823.83  371.76  823.35  374.28  824.94  379.35  827.04
  452.06  831.44  461.46   831.5  488.78  828.76  514.83  828.97  573.34  827.91
  713.31  829.65  817.35  834.41  885.68  835.31  928.02  837.06  985.27  848.35
 1013.54  855.77 1097.41  863.36 1130.76  868.51 1208.67  873.86 1269.72  874.37
#Mann= 13 ,-1,0
       0     .03       0   93.68      .1       0  338.01     .07       0
  349.28     .06       0  374.28     .07       0  379.35      .1       0
  452.06    .013       0  461.46      .1       0  514.83    .035       0
  713.31      .1       0  817.35    .013       0  885.68      .1       0
 1269.72      .1       0
#XS Ineff= 4 ,-1
      59      93     855     190     239     850     239     338   829.2
     460     775   831.9
Permanent Ineff=
       T       T       F       F
Bank Sta=338.01,379.35
XS Rating Curve= 0 ,0
Exp/Cntr=0.3,0.1

Type RM Length L Ch R = 1 ,492.3110,0,0,0
XS GIS Cut Line= 4
1564454.95419805 633357.344058491564809.86885585 633347.68016858
1564840.56942751 633335.939753781565357.78606478 633283.10788714
#Sta/Elev= 30
       0  834.39   24.38  834.78  125.86  832.23   174.6  827.66   241.3  828.28
   327.5  827.84  345.67   827.7  359.78  828.82  361.75  828.38  366.71  823.68
  390.68  822.68   394.2  822.61   400.8  827.26  458.72  831.42  471.51  831.35
  496.09  827.76  513.78  828.58  543.29   828.3  612.96  830.03  628.03  829.45
  649.54  830.89  657.36  831.26  667.64  829.51  703.79  831.96  746.75  833.02
  782.74  832.92  802.27  830.83  835.98  829.51  874.97   829.7  907.63  831.79
#Mann= 13 ,-1,0
       0     .03       0   327.5      .1       0  359.78     .07       0
  366.71     .06       0  390.68     .07       0   400.8      .1       0
  458.72    .013       0  471.51      .1       0  513.78    .035       0
  649.54      .1       0  703.79    .013       0  782.74      .1       0
  907.63      .1       0
#XS Ineff= 2 ,-1
     465     705   831.8     765  907.82   833.2
Permanent Ineff=
       F       T
Bank Sta=359.78,400.8
XS Rating Curve= 0 ,0
Exp/Cntr=0.3,0.1
LCMann Table=0

Chan Stop Cuts=-1
Use User Specified Reach Order=0
Composite Channel Slope=5

--- GRE-68TAF.g02 (geometry) ---

Geom Title=ExistingTAF2
Program Version=6.41

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
River Reach=Oldtown Creek   ,Reach

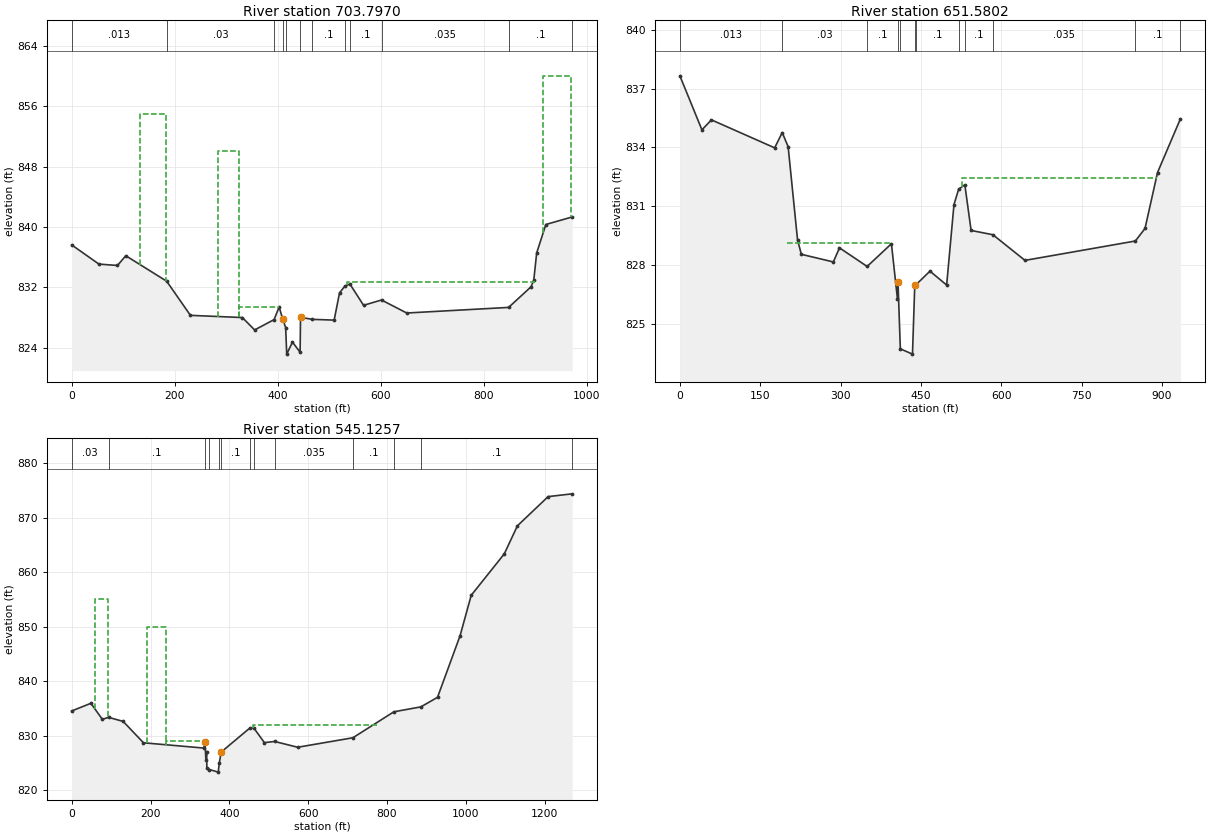
Type RM Length L Ch R = 1 ,703.7970,56.86,52.22,53.96
XS GIS Cut Line= 4
1564351.57189531 633170.133788931564742.66198021 633142.73948771
1564799.61447382 633134.423360561565307.72604505 633015.41407765
#Sta/Elev= 30
       0  837.63   52.88  835.09   88.91  834.91  104.99   836.2  184.32  832.83
  230.47  828.31  331.27  828.02   355.1  826.38  392.91  827.75  402.62  829.42
  409.74  827.79  415.29   826.7  417.35  823.18  428.51  824.77  443.35  823.43
  444.18  828.05   467.2  827.78  509.44  827.68  519.88  831.29  530.18  832.17
     540  832.45  566.53  829.64   601.4  830.34  650.33  828.62  848.05  829.36
  891.48  832.08  896.83  832.94  902.53  836.57  920.35  840.33  971.47  841.33
#Mann= 12 ,-1,0
       0    .013       0  184.32     .03       0  392.91      .1       0
  409.74     .07       0  415.29     .06       0  443.35     .07       0
   467.2      .1       0  530.18    .013       0     540      .1       0
   601.4    .035       0  848.05      .1       0  971.47      .1       0
#XS Ineff= 5 ,-1
     133     184     855     284     325     850     325   402.5   829.4
     535     900  832.73     915     970     860
Permanent Ineff=
       T       T       F       T       T
Bank Sta=409.74,444.18
XS Rating Curve= 0 ,0
Exp/Cntr=0.3,0.1

Type RM Length L Ch R = 1 ,651.5802,111.44,106.45,103.86
XS GIS Cut Line= 4
1564368.19322392 633223.944023461564754.39468275 633194.59298644
1564803.28094337 633185.787675341565298.98762597 633146.65295931
#Sta/Elev= 30
       0  837.66   41.14   834.9    58.9  835.41  176.92  833.98  191.05  834.76
  202.06  834.04  219.65  829.27  226.73  828.54  286.43  828.15  297.93  828.87
  349.54  827.92  394.87  829.08  406.18  826.24  407.14  827.12  411.51  823.71
  434.17  823.44  438.42  826.95  440.53  826.98  466.79  827.68  497.94  826.97
  511.62  831.08  520.34  831.87  531.91  832.09  543.58  829.76  584.31  829.54
  644.17  828.23  850.17  829.22  868.19  829.86  891.58  832.72  934.24  835.46
#Mann= 12 ,-1,0
       0    .013       0  191.05     .03       0  349.54      .1       0
  407.14     .07       0  411.44     .06       0  438.42     .07       0
  440.53      .1       0  520.34    .013       0  531.91      .1       0
  584.31    .035       0  850.17      .1       0  934.24      .1       0
#XS Ineff= 2 ,-1
     200     395   829.1     526     891  832.46
Permanent Ineff=
       F       F
Bank Sta=407.14,438.42
XS Rating Curve= 0 ,0
Exp/Cntr=0.3,0.1

Type RM Length L Ch R = 1 ,545.1257,46.6,52.81,53.82
XS GIS Cut Line= 2
1564453.88126293  633319.22246731565720.03325592 633224.16122113
#Sta/Elev= 30
       0  834.56   48.72  835.97   77.73  833.03   93.68  833.39  130.52  832.65
  182.09  828.73  335.39  827.76  338.01  828.94  340.42   825.6  342.39  827.13
  342.86  824.13  349.28  823.83  371.76  823.35  374.28  824.94  379.35  827.04
  452.06  831.44  461.46   831.5  488.78  828.76  514.83  828.97  573.34  827.91
  713.31  829.65  817.35  834.41  885.68  835.31  928.02  837.06  985.27  848.35
 1013.54  855.77 1097.41  863.36 1130.76  868.51 1208.67  873.86 1269.72  874.37
#Mann= 13 ,-1,0
       0     .03       0   93.68      .1       0  338.01     .07       0
  349.28     .06       0  374.28     .07       0  379.35      .1       0
  452.06    .013       0  461.46      .1       0  514.83    .035       0
  713.31      .1       0  817.35    .013       0  885.68      .1       0
 1269.72      .1       0
#XS Ineff= 4 ,-1
      59      93     855     190     239     850     239     338   829.1
     460     775   831.9
Permanent Ineff=
       T       T       F       F
Bank Sta=338.01,379.35
XS Rating Curve= 0 ,0
Exp/Cntr=0.3,0.1